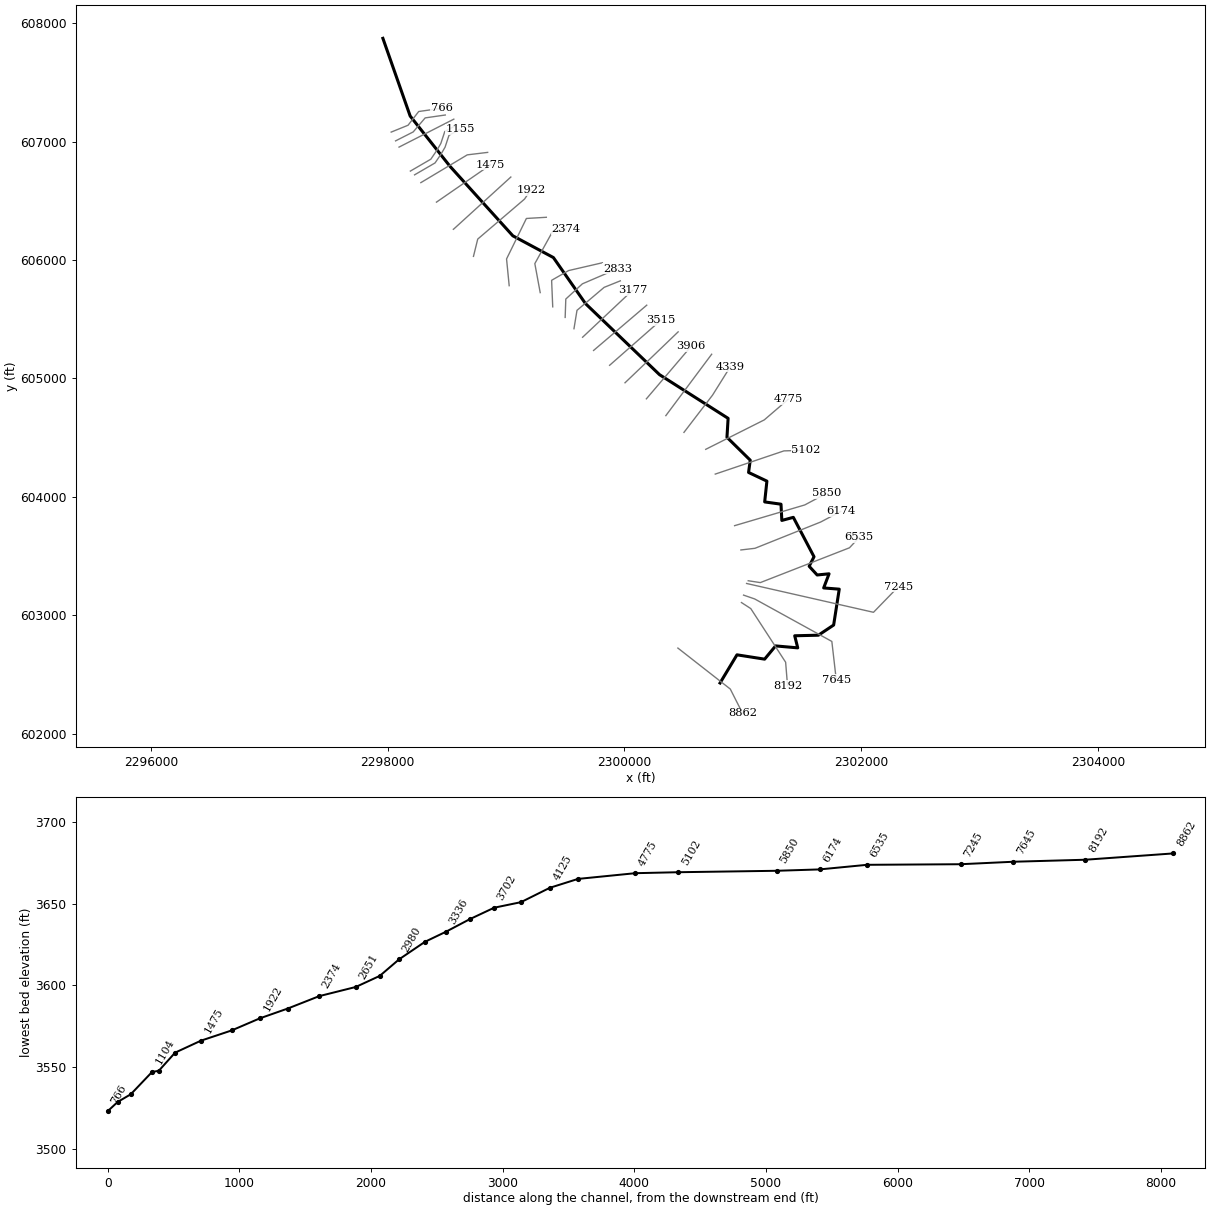
--- GLADERN.prj (project) ---

Proj Title=GLADERN
Current Plan=p01
Default Exp/Contr=0,0
English Units
Geom File=g01
Flow File=f01
Plan File=p01
BEGIN DESCRIPTION:
----------MODEL BY WOOD PLC 2022----------
AFH study
Randolph County, WV
HEC-RAS Version: RAS 6.2
Vertical Datum: NAVD88
Projection: NAD 1983 StatePlane West Virginia S FIPS 4702 (US Feet)
Terrain: 1-meter LIDAR (FEMA Region III 3DEP collected 2016-2018)
Land Use: 2019 NLCD
Hydrologic Method:
WV SIR2010-5033 regression equations
Additional Model Notes:
None
END DESCRIPTION:
DSS Export Rating Curves= 0
DSS Export Rating Curve Sorted= 0
DSS Export Volume Flow Curves= 0
DXF OffsetX= 0
DXF OffsetY= 0
DXF ScaleX= 0
DXF ScaleY= 0

--- GLADERN.p01 (plan) ---

Plan Title=Floodplain
Program Version=6.20
Short Identifier=Floodplain
Geom File=g01
Flow File=f01
Subcritical Flow
K Sum by GR= 0
Std Step Tol= 0.01
Critical Tol= 0.01
Num of Std Step Trials= 20
Max Error Tol= 0.3
Flow Tol Ratio= 0.001
Split Flow NTrial= 30
Split Flow Tol= 0.02
Split Flow Ratio= 0.02
Log Output Level= 0
Friction Slope Method= 1
Unsteady Friction Slope Method= 2
Unsteady Bridges Friction Slope Method= 1
Parabolic Critical Depth
Global Vel Dist= 0 , 0 , 0
Global Log Level= 0
CheckData=True
Encroach Param=-1 ,0,0, 0
Mapping Interval=1HOUR
Computation Time Step Use Courant=        0
Computation Time Step Use Time Series=    0
Computation Time Step Count To Double=0
Computation Time Step Max Doubling=0
Computation Time Step Max Halving=0
Computation Time Step Residence Courant=0
Run HTab= 0
Run UNet= 0
Run Sediment= 0
Run PostProcess= 0
Run WQNet= 0
Run RASMapper= 0
UNET Theta= 0
UNET Theta Warmup= 0
UNET ZTol= 0
UNET ZSATol= 0
UNET MxIter= 0
UNET Max Iter WO Improvement= 0
UNET MaxInSteps= 0
UNET DtIC= 0
UNET DtMin= 0
UNET MaxCRTS= 0
UNET WFStab= 0
UNET SFStab= 0
UNET WFX= 1
UNET SFX= 1
UNET Gravity=32.174
UNET 1D Methodology=Finite Difference
UNET DSS MLevel= 1
UNET Pardiso=0
UNET DZMax Abort= 0
UNET Use Existing IB Tables= 0
UNET Froude Reduction=False
UNET Froude Limit= 0
UNET Froude Power= 0
UNET D1 Cores= 0
UNET WindReference=Eulerian
UNET WindDragFormulation=Hsu (1988)
UNET D2 Coriolis=0
UNET D2 Cores= 0
UNET D2 Theta= 1
UNET D2 Theta Warmup= 1
UNET D2 Z Tol= 0.01
UNET D2 Volume Tol= 0.01
UNET D2 Max Iterations= 20
UNET D2 Equation= 0
UNET D2 RampUpFraction=0.1
UNET D2 TimeSlices= 1
UNET D2 Turbulence Formulation=Non-Conservative (original)
UNET D2 Eddy Viscosity=0.3
UNET D2 Transverse Eddy Viscosity=0.1
UNET D2 Smagorinsky Mixing=0
UNET D2 BCVolumeCheck=0
UNET D2 Cores=0
UNET D2 SolverType=PARDISO (Direct)
UNET D2 Minimum Iterations= 2147483647
UNET D2 Maximum Iterations= 2147483647
UNET D2 Restart Number= 10
UNET D2 Relaxation Coeff=1.3
UNET D2 SOR Precondition Iterations= 10
UNET D2 ILUT Maximum Fill= 8
UNET D2 ILUT Tolerance=1E-08
UNET D1D2 MaxIter= 0
UNET D1D2 ZTol=0.01
UNET D1D2 QTol=0.1
UNET D1D2 MinQTol=1
Write IC File= 0
Write IC File at Fixed DateTime=0
Write IC File at Sim End=0
Echo Input=False
Echo Parameters=False
Echo Output=False
Write Detailed= 0
HDF Write Warmup=0
HDF Write Time Slices=0
HDF Flush=0
HDF Compression= 1
HDF Chunk Size= 1
HDF Spatial Parts= 1
HDF Use Max Rows=0
HDF Fixed Rows= 1
Calibration Method= 0
Calibration Iterations= 20
Calibration Max Change=0.05
Calibration Tolerance=0.2
Calibration Maximum=1.5
Calibration Minimum=0.5
Calibration Optimization Method= 1
WQ AD Non Conservative
WQ ULTIMATE=-1
WQ Max Comp Step=1HOUR
WQ Output Interval=15MIN
WQ Output Selected Increments= 0
WQ Output face flow=0
WQ Output face velocity=0
WQ Output face area=0
WQ Output face dispersion=0
WQ Output cell volume=0
WQ Output cell surface area=0
WQ Output cell continuity=0
WQ Output cumulative cell continuity=0
WQ Output face conc=0
WQ Output face dconc_dx=0
WQ Output face courant=0
WQ Output face peclet=0
WQ Output face adv mass=0
WQ Output face disp mass=0
WQ Output cell mass=0
WQ Output cell source sink temp=0
WQ Output nsm pathways=0
WQ Output nsm derived pathways=0
WQ Create Restart=0
WQ Fixed Restart=0
WQ System Summary=0
WQ Write To DSS=0
Sorting and Armoring Iterations= 10
XS Update Threshold= 0.02
Bed Roughness Predictor= 0
Hydraulics Update Threshold= 0.02
Energy Slope Method= 1
Volume Change Method= 1
Sediment Retention Method= 0
Sediment TS Multiplier= 1
Warm Up Method= 0
XS Weighting Method= 0
Number of US Weighted Cross Sections= 1
Number of DS Weighted Cross Sections= 1
Upstream XS Weight=0
Main XS Weight=1
Downstream XS Weight=0
Number of DS XS's Weighted with US Boundary= 1
Upstream Boundary Weight= 1
Weight of XSs Associated with US Boundary= 0
Number of US XS's Weighted with DS Boundary= 1
Downstream Boundary Weight= 0.5
Weight of XSs Associated with DS Boundary= 0.5
Percentile Method= 0
Sediment Output Level= 3
Mass or Volume Output= 0
Output Increment Type= 1
Profile and TS Output Increment= 1
Transport Output Increment 1
XS Output Flag= 0
XS Output Increment= 10
Read HDF5 Sediment Hotstart= 0
Sediment Hotstart Type= 0
Write Gradation File= 0
Read Gradation Hotstart= 0
Write HDF5 File= 1
Write Binary Output= 1
Write DSS Sediment File= 0
DSS Sediment Output Type= 1
SV Curve= 0
Specific Gage Flag= 0
Subcell Erosion Methods= 0
Subcell Deposition Methods= 0
Advection Scheme= 1
Matrix Solver= 0
Implicit Weighting Factor= 1
Maximum Outer Loop Convergence Iterations= 5
Convergence Maximum Absolute= 0.001
Convergence RMSE= 0.0001
Grain Fractions Max Abs Error= 0.001
Max Subgrid Regions= 1
Max Subgrid Length Scale= 3.402823E+38
Initial Layer Thickness= 3.402823E+38
Min Layer Thickness= 3.402823E+38
Max Layer Thickness= 3.402823E+38
Number of Layers= 5

--- GLADERN.f01 (steady flow) ---

Flow Title=Flow
Program Version=4.00
Number of Profiles=1
Profile Names=P100yr
River Rch & RM=GLADERN,Main,8862
     401
River Rch & RM=GLADERN,Main,2374
     447
River Rch & RM=GLADERN,Main,1708
     516
Boundary for River Rch & Prof#=GLADERN,Main      ,1
Up Type=0
Dn Type=3
Dn Slope=0.039659

--- GLADERN.g01 (geometry) ---

Geom Title=Geometry
Program Version=6.20

River Reach=GLADERN         ,Main
Reach XY= 30
     2300807.251      602428.155     2300950.237      602666.098
     2301183.823      602629.603     2301276.373      602741.378
     2301463.412      602724.942     2301437.888      602827.045
2301637.96188762602831.825002855      2301766.67      602917.666
     2301813.979      603220.617     2301682.468      603231.034
     2301728.041      603350.391     2301627.346      603340.409
2301559.89290184603414.143441288     2301600.871      603494.489
     2301426.262      603827.193     2301329.039      603801.151
     2301322.095      603938.304     2301184.248      603957.401
     2301202.998      604133.096     2301048.137       604206.36
     2301062.373      604309.8312300865.74589036604503.237621233
     2300875.385      604663.3692300295.92097914605032.371975661
     2299670.784      605632.544     2299399.985      606021.121
     2299057.277      606204.975     2298526.209       606792.34
 2298190.1942491607216.647619455     2297959.822      607872.658

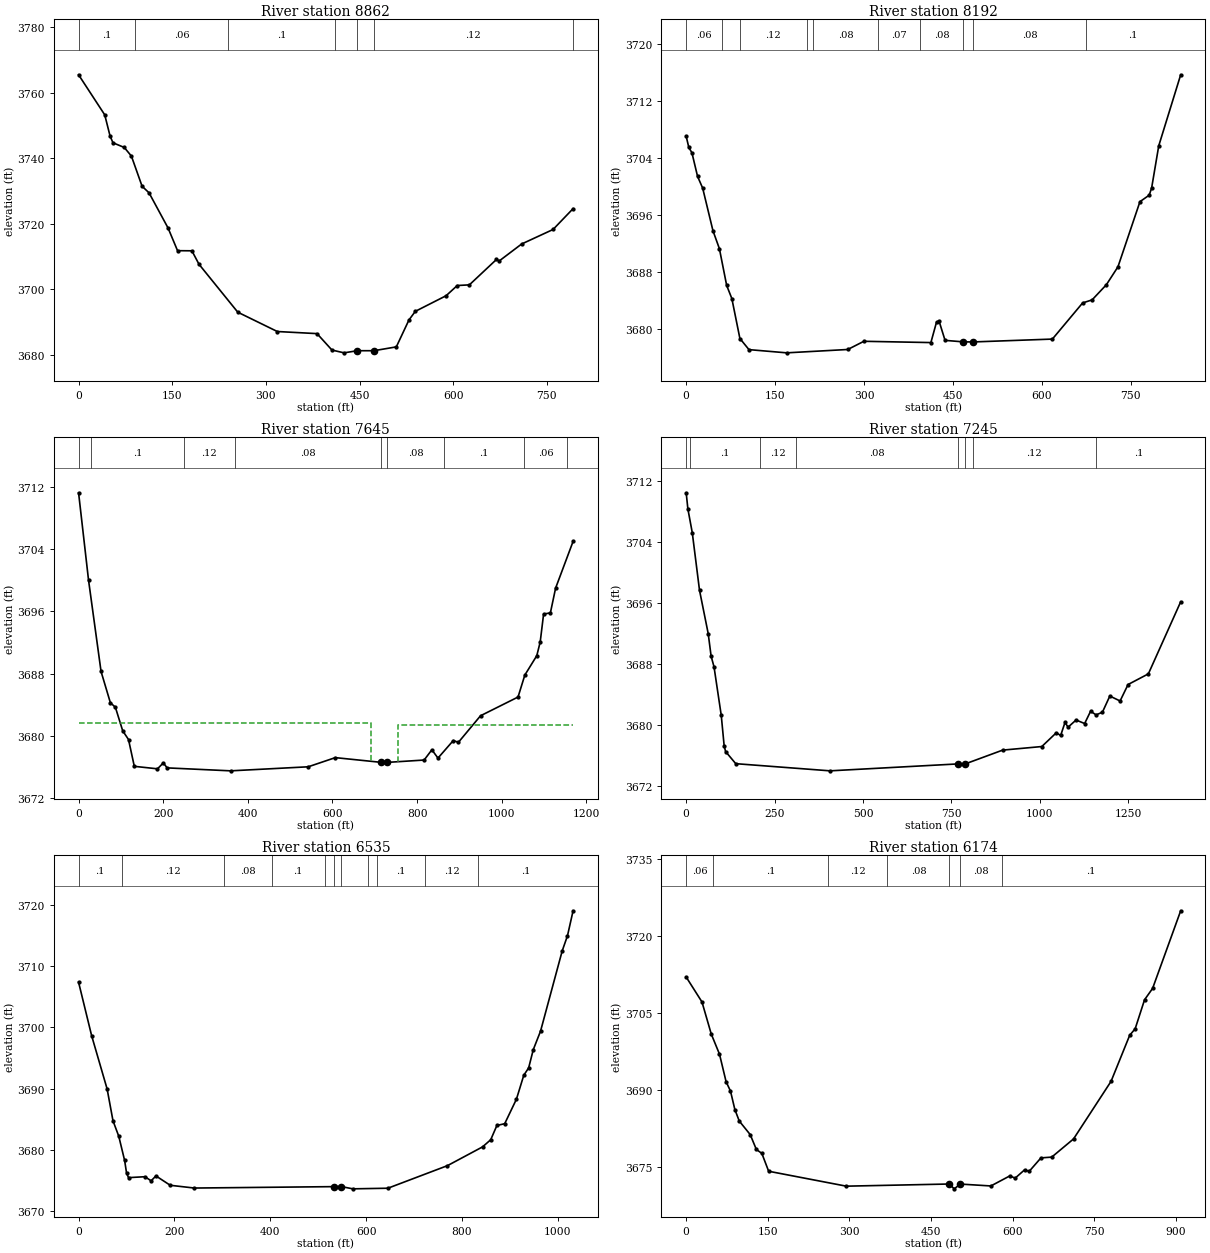
Type RM Length L Ch R = 1 ,8862    ,673.3,669.2,662.4
XS GIS Cut Line= 3
2300451.31034398602723.1282897092300893.82040082602377.101549868
2300997.87380046602171.637728657
#Sta/Elev= 30
       0  3765.5    41.9 3753.26    50.4 3746.81    55.1 3744.73    73.2  3743.3
    84.6 3740.67   101.7 3731.46   112.8 3729.46   143.3 3718.71   158.5 3711.78
   181.5 3711.74   192.9 3707.62     255 3692.99   318.3 3687.09   381.9 3686.45
   405.8 3681.43   425.2 3680.58   446.5 3681.23  472.943681.229   508.9  3682.4
   529.1 3690.61   539.3 3693.25   588.6 3698.02   606.5 3701.14   625.9 3701.34
   669.3  3709.1   673.7 3708.64   709.6 3713.82   759.9 3718.25     792 3724.62
#Mann= 7 ,-1,0
       0      .1       0      90     .06       0     240      .1       0
     410     .12       0   446.5    .045       0  472.94     .12       0
  791.74      .1       0
Bank Sta=446.5,472.94
XS Rating Curve= 0 ,0
Exp/Cntr=0.3,0.1

Type RM Length L Ch R = 1 ,8192    ,542.5,547.2,545.4
XS GIS Cut Line= 4
2300988.06888842603107.5808749712301066.85849304603056.599366099
2301361.16083971602603.5591395312301377.38222889602404.267786667
#Sta/Elev= 30
       0  3707.1     4.4 3705.55     9.7 3704.78    19.2 3701.47    27.8 3699.83
    45.2 3693.84      56 3691.34    68.3 3686.17      77 3684.34    90.6 3678.73
   105.9 3677.17   169.5 3676.72   272.5 3677.19   299.7 3678.34   412.7 3678.16
   422.3 3681.06   426.7 3681.12   436.6 3678.47   467.4 3678.26   484.3 3678.25
   617.6 3678.65   668.6 3683.72   684.6 3684.15   708.7 3686.28   728.2 3688.79
   765.3 3697.93   780.9 3698.84     785 3699.85     797 3705.77     834 3715.73
#Mann= 10 ,-1,0
       0     .06       0      60      .1       0      90     .12       0
  203.85      .1       0  213.85     .08       0  323.85     .07       0
  393.85     .08       0   467.4    .045       0   484.3     .08       0
  674.09      .1       0
Bank Sta=467.4,484.3
XS Rating Curve= 0 ,0
Exp/Cntr(USF)=0,0
Exp/Cntr=0.3,0.1

Type RM Length L Ch R = 1 ,7645    ,382.8,400.4,388.3
BEGIN DESCRIPTION:
IFAs needed to wet channel
END DESCRIPTION:
XS GIS Cut Line= 4
 2301005.9686781603170.4264373862301099.49369785603138.195278125
2301751.49320079602779.1970507592301788.66171137602455.935134481
#Sta/Elev= 30
       0 3711.28    23.5 3700.05    53.1 3688.28    75.1 3684.26      87 3683.67
   104.3 3680.64     118 3679.52   131.7 3676.07   186.5 3675.75   200.2 3676.51
   209.3 3675.87   359.3 3675.49   542.6 3676.01   606.7 3677.19   715.6 3676.58
   729.8 3676.58   816.6 3676.88   834.9  3678.2   849.3 3677.13   885.5 3679.39
   897.6 3679.16   949.9 3682.58  1038.5 3684.99  1054.6 3687.82  1082.8 3690.31
  1090.9 3692.08  1098.9 3695.66    1115 3695.83  1127.3 3699.01  1168.6 3705.02
#Mann= 9 ,-1,0
       0     .06       0      30      .1       0  248.92     .12       0
  368.92     .08       0   715.6    .045       0   729.8     .08       0
  863.22      .1       0 1053.22     .06       0 1153.22      .1       0
#XS Ineff= 2 , 0
          690.54 3681.69  753.79         3681.41
Permanent Ineff=
       F       F
Bank Sta=715.6,729.8
XS Rating Curve= 0 ,0
Exp/Cntr=0.3,0.1

Type RM Length L Ch R = 1 ,7245    ,672.4,709.8,684.5
XS GIS Cut Line= 3
2301031.44739147603268.6686662312302103.25688585603025.281742965
2302311.87424865603239.945985846
#Sta/Elev= 30
       0 3710.48     4.8 3708.36    17.2 3705.25    37.7 3697.68    62.3 3691.99
    70.5 3689.03    78.7 3687.64    99.2 3681.25   107.4 3677.25   111.5 3676.51
   140.2 3674.92   406.8 3673.98     769 3674.89   789.1 3674.89   894.9  3676.7
  1005.7 3677.17  1046.7 3678.98    1059 3678.62  1071.3 3680.34  1079.9 3679.71
  1102.5 3680.65  1126.8 3680.19  1143.6  3681.8  1159.1 3681.33    1177 3681.67
    1198  3683.8    1227 3683.15  1249.6 3685.31    1307 3686.71  1398.4 3696.17
#Mann= 8 ,-1,0
       0     .06       0      10      .1       0     210     .12       0
     310     .08       0     769    .045       0   789.1     .08       0
     810     .12       0  1159.1      .1       0
Bank Sta=769,789.1
XS Rating Curve= 0 ,0
Exp/Cntr(USF)=0,0
Exp/Cntr=0.3,0.1

Type RM Length L Ch R = 1 ,6535    ,354.4,361.4,353.5
XS GIS Cut Line= 4
2301045.22769446603291.7283178192301147.42244633603276.086263961
2301900.32663872  603570.15687652301982.70812238603657.752378107
#Sta/Elev= 30
       0 3707.37    27.3 3698.62    59.6 3689.92    71.8 3684.74    83.9  3682.2
    96.1 3678.25   100.1 3676.21   104.2 3675.45   138.5  3675.6   151.4 3674.93
   161.4 3675.73   191.3  3674.2   241.6 3673.75  532.36 3673.98  548.013673.993
   572.3 3673.62   645.4 3673.72   769.8 3677.41   842.9 3680.47     860 3681.64
   872.9 3683.97   889.2 3684.26   913.7 3688.27     929 3692.17   939.2 3693.38
   948.8 3696.35     964 3699.38  1009.2 3712.49  1020.2 3714.96  1031.9 3719.04
#Mann= 11 ,-1,0
       0      .1       0      90     .12       0  303.38     .08       0
  403.38      .1       0  513.38     .12       0  532.36    .045       0
  548.01     .12       0  603.38     .08       0  623.38      .1       0
  723.38     .12       0  833.38      .1       0
Bank Sta=532.36,548.01
XS Rating Curve= 0 ,0
Exp/Cntr(USF)=0,0
Exp/Cntr=0.3,0.1

Type RM Length L Ch R = 1 ,6174    ,324,324,324
XS GIS Cut Line= 4
2300983.37432175603551.7837886872301102.28460339603565.791625223
2301657.13980755603787.7122764222301826.14644254603876.911169851
#Sta/Elev= 30
       0    3712      29 3707.16    46.1 3700.91    61.2    3697    73.3 3691.65
    81.4 3689.82    89.4 3686.24    97.5    3684   117.6 3681.36   128.9 3678.47
     139  3677.7   151.5 3674.23   294.1 3671.33   483.6 3671.75   492.3 3670.81
  503.693671.737   559.7 3671.37   594.6 3673.33   604.3 3672.89   621.5 3674.49
   630.1 3674.21   651.7 3676.83   671.5 3676.98   711.6 3680.52   780.5 3691.72
   814.7 3700.67   824.8 3701.95     842 3707.58   856.8 3709.79   908.4 3724.89
#Mann= 7 ,-1,0
       0     .06       0      50      .1       0  259.73     .12       0
  369.73     .08       0   483.6    .045       0  503.69     .08       0
  579.73      .1       0
Bank Sta=483.6,503.69
XS Rating Curve= 0 ,0
Exp/Cntr=0.3,0.1

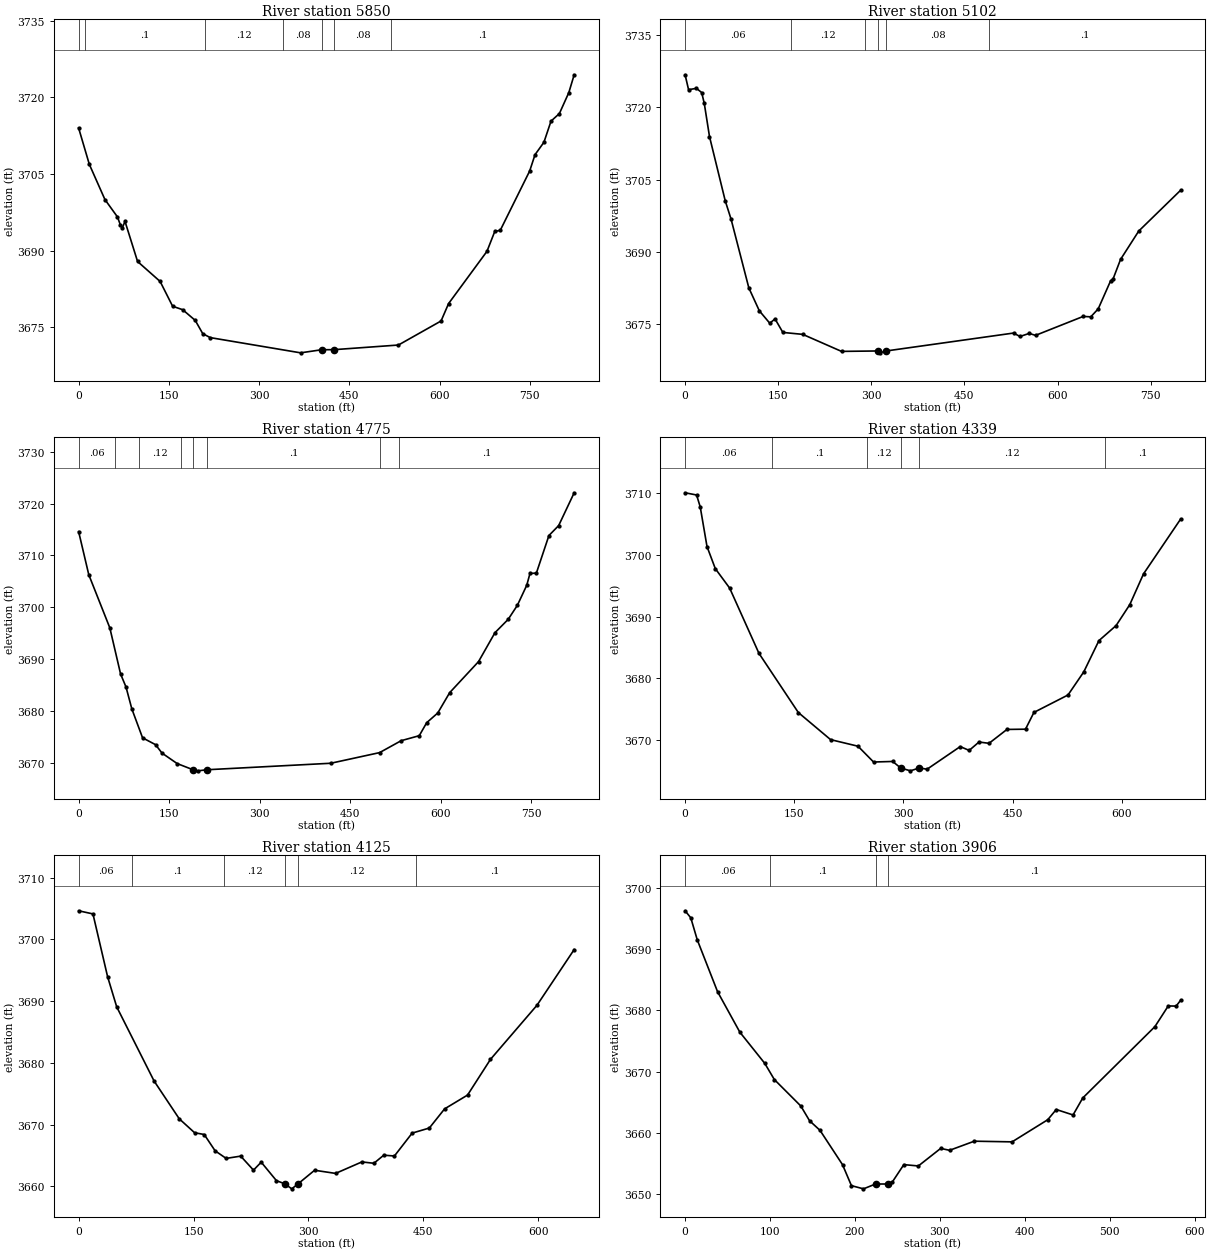
Type RM Length L Ch R = 1 ,5850    ,748,748,748
XS GIS Cut Line= 3
2300930.23245528603756.9523480852301522.74657824 603931.96842634
2301704.68057571 604028.74390348
#Sta/Elev= 30
       0 3714.01    17.8 3706.89    43.7 3700.01    64.6 3696.59    69.4 3695.03
    72.9 3694.52    77.1 3695.73      98 3687.87   135.5 3683.96   156.3  3679.1
     173 3678.43   193.9 3676.33   206.4 3673.73   218.9 3672.96   369.1 3669.98
   404.2 3670.59   424.4  3670.6   531.7 3671.51   602.6 3676.22   615.1 3679.63
   678.9 3689.86   691.9 3693.76     701 3693.97   749.9 3705.59   758.8 3708.79
   773.6 3711.22   785.4 3715.36   799.3 3716.84     815 3720.95   823.9 3724.44
#Mann= 7 ,-1,0
       0     .06       0      10      .1       0     210     .12       0
     340     .08       0   404.2    .045       0   424.4     .08       0
     520      .1       0
Bank Sta=404.2,424.4
XS Rating Curve= 0 ,0
Exp/Cntr=0.3,0.1

Type RM Length L Ch R = 1 ,5102    ,323.8,327.1,325.6
XS GIS Cut Line= 3
2300766.91312043604192.5171641182301346.90304268604388.452963408
2301532.95132063604393.832398884
#Sta/Elev= 30
       0 3726.73     5.6 3723.64    18.2 3723.92    26.7 3723.05    30.9  3720.8
    39.3 3713.93    64.7 3700.59    74.1 3696.79   102.7 3682.55   119.6 3677.81
   136.4 3675.24   144.9 3676.13   157.5 3673.33   189.5 3672.93     252  3669.4
   310.73669.489     314  3669.1   323.4 3669.48   529.1  3673.2   539.5 3672.49
   554.4 3673.13   564.5 3672.72   641.4 3676.65   653.5 3676.56   665.5 3678.21
   685.5 3684.03   689.5 3684.43   701.5 3688.46   730.8 3694.34   798.3  3702.8
#Mann= 6 ,-1,0
       0     .06       0     170     .12       0     290     .08       0
   310.7    .045       0   323.4     .08       0     490      .1       0
Bank Sta=310.7,323.4
XS Rating Curve= 0 ,0
Exp/Cntr=0.3,0.1

Type RM Length L Ch R = 1 ,4775    ,422,435.8,433.4
XS GIS Cut Line= 3
2300686.39131866604401.6138744442301180.88828302604650.192121947
2301383.66072002604824.412522353
#Sta/Elev= 30
       0 3714.59    16.8 3706.29    51.7 3696.04    69.5 3687.16    78.5 3684.65
    88.1 3680.45   105.9 3674.87   127.4 3673.55   138.1 3671.93   163.2 3669.91
     190  3668.7   197.6 3668.51   212.5 3668.72   417.6 3669.97   498.5 3672.02
   534.3 3674.32   564.2 3675.28   576.5 3677.78   594.9 3679.66   614.6 3683.57
   662.4 3689.55   689.6 3695.12   711.5 3697.69   726.6 3700.37   742.2 3704.24
   747.6 3706.53   758.2  3706.6     779 3713.84   795.1 3715.75   820.8 3722.07
#Mann= 8 ,-1,0
       0     .06       0      60      .1       0     100     .12       0
     170      .1       0     190    .045       0   212.5      .1       0
     500     .12       0     530      .1       0
Bank Sta=190,212.5
XS Rating Curve= 0 ,0
Exp/Cntr=0.3,0.1

Type RM Length L Ch R = 1 ,4339    ,213.3,213.7,213.9
XS GIS Cut Line= 3
2300502.48360162 604544.664401422300743.89092174604859.253680385
2300894.77668039605100.384158539
#Sta/Elev= 30
       0 3710.07    15.8 3709.71    20.8 3707.78    30.1 3701.36    41.5 3697.78
    61.2 3694.63   101.5 3684.05   155.6 3674.46   199.9 3670.07   237.6    3669
     259 3666.44   285.3 3666.53  296.29 3665.47   309.7 3665.01  321.873665.485
   332.5 3665.27   378.1 3668.94   390.4 3668.32   403.9 3669.68   417.7 3669.47
   442.3 3671.72   467.8 3671.76   479.4 3674.48   526.2  3677.3   547.9 3681.05
   568.7 3686.11   592.3 3688.55   611.1 3691.94     630 3696.93     681 3705.81
#Mann= 6 ,-1,0
       0     .06       0     120      .1       0     250     .12       0
  296.29    .045       0  321.87     .12       0  576.54      .1       0
Bank Sta=296.29,321.87
XS Rating Curve= 0 ,0
Exp/Cntr=0.3,0.1

Type RM Length L Ch R = 1 ,4125    ,218.2,219.4,218
XS GIS Cut Line= 2
2300349.58996019604686.2318324472300736.59028538605204.751799405
#Sta/Elev= 30
       0 3704.63    18.7 3704.12    37.8 3693.96    49.7 3689.07    98.5 3677.06
   131.4 3670.93   151.4 3668.68     164 3668.39   178.2 3665.75   192.6 3664.52
   211.6 3664.89   228.3 3662.62   238.4 3663.91   258.3 3660.91  269.113660.411
   278.3 3659.59   286.9 3660.44   308.1  3662.6   335.5 3662.09   369.8 3663.95
   385.5 3663.73   398.4 3665.04   412.3 3664.91   435.5 3668.62   457.9 3669.44
   477.8 3672.54   507.8 3674.78   537.7 3680.56   598.4 3689.32     647 3698.35
#Mann= 6 ,-1,0
       0     .06       0      70      .1       0     190     .12       0
  269.11    .045       0   286.9     .12       0     440      .1       0
Bank Sta=269.11,286.9
XS Rating Curve= 0 ,0
Exp/Cntr(USF)=0,0
Exp/Cntr=0.3,0.1

Type RM Length L Ch R = 1 ,3906    ,203.7,203.4,202.6
XS GIS Cut Line= 2
2300185.10805228604828.075625696 2300563.6071333605272.232710565
#Sta/Elev= 30
       0 3696.28     6.7 3695.13    14.3 3691.54    38.2 3683.06    64.5 3676.43
    93.8 3671.34   105.1 3668.69   136.3 3664.36   146.6 3661.95   158.9 3660.38
   185.4 3654.77   195.9 3651.34   210.1 3650.82   224.3 3651.61   239.1 3651.61
   244.1 3651.95   257.6 3654.78   274.7 3654.56     301 3657.43   311.5 3657.12
   340.6 3658.61   385.1  3658.5   427.1 3662.12   437.1 3663.79   456.9  3662.9
   468.3 3665.67   553.3 3677.34     569 3680.72   578.3  3680.7   583.6 3681.65
#Mann= 4 ,-1,0
       0     .06       0     100      .1       0   224.3    .045       0
   239.1      .1       0
Bank Sta=224.3,239.1
XS Rating Curve= 0 ,0
Exp/Cntr(USF)=0,0
Exp/Cntr=0.3,0.1

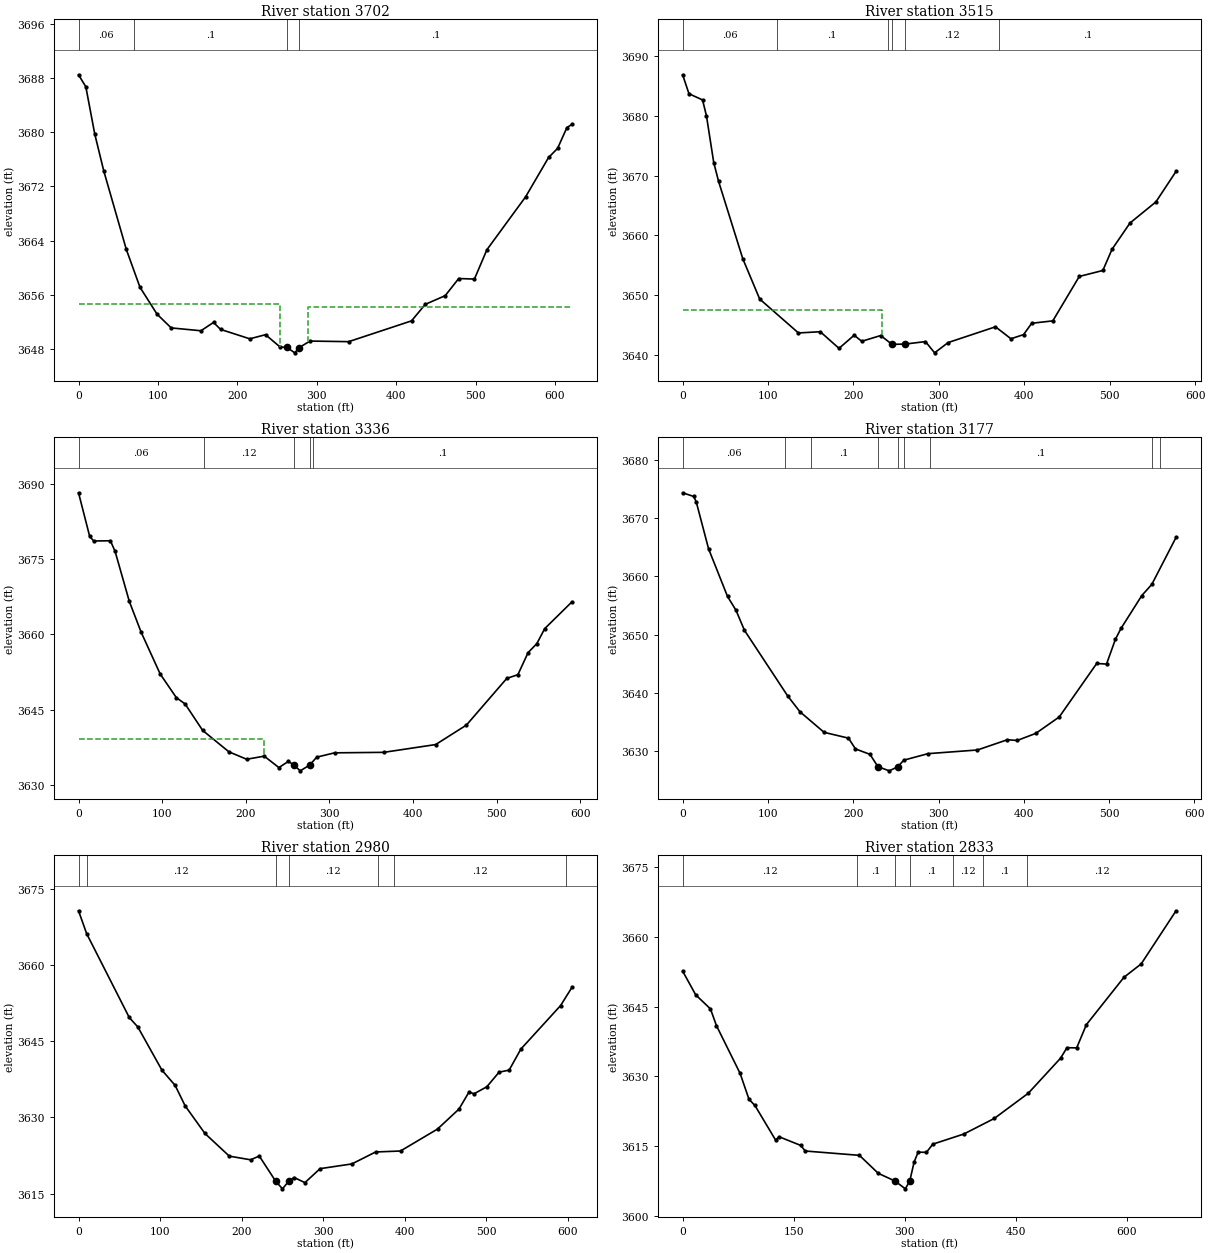
Type RM Length L Ch R = 1 ,3702    ,187,186.8,186
XS GIS Cut Line= 3
2300004.67689472 604963.697668792300244.82397297605193.228348161
2300453.38681139605393.574906599
#Sta/Elev= 30
       0 3688.49     9.2 3686.72    20.5 3679.71    31.8 3674.29    60.2  3662.7
    77.4 3657.12    98.9 3653.15   116.7 3651.12   154.2  3650.7     170 3651.93
   178.9  3650.9   215.7 3649.51   235.5 3650.12   253.8 3648.31   262.7 3648.23
   272.3 3647.44   277.9 3648.22   291.6 3649.18   340.2 3649.09   419.4 3652.16
   436.7  3654.6   461.8 3655.88   478.8 3658.41   498.6 3658.33   514.3 3662.66
   563.1 3670.48     592 3676.28   603.3 3677.62   615.1  3680.7   621.4 3681.17
#Mann= 4 ,-1,0
       0     .06       0      70      .1       0   262.7    .045       0
   277.9      .1       0
#XS Ineff= 2 , 0
          253.21 3654.66   289.1         3654.14
Permanent Ineff=
       F       F
Bank Sta=262.7,277.9
XS Rating Curve= 0 ,0
Exp/Cntr=0.3,0.1

Type RM Length L Ch R = 1 ,3515    ,179.7,179.4,179.4
XS GIS Cut Line= 2
2299874.65107111 605111.353912462300308.55654318 605492.80927252
#Sta/Elev= 30
       0 3686.83     7.4 3683.66    23.3 3682.63    27.9 3679.96    36.4 3672.17
    42.1 3669.01    70.4 3656.11    90.2 3649.37   135.6  3643.7   161.1 3643.91
   183.1 3641.13   200.8 3643.32   209.7 3642.31   231.9 3643.27   245.1  3641.8
   260.3 3641.84   284.3 3642.26     295 3640.38   310.9  3642.1   366.3 3644.73
   384.4 3642.73   399.2 3643.43   408.7 3645.32   433.4 3645.72   464.4 3653.14
     492 3654.14   502.7 3657.67   523.8 3662.07   554.1 3665.59   577.7 3670.69
#Mann= 6 ,-1,0
       0     .06       0     110      .1       0     240     .12       0
   245.1    .045       0   260.3     .12       0     370      .1       0
#XS Ineff= 2 , 0
           233.5  3647.5
Permanent Ineff=
       F       F
Bank Sta=245.1,260.3
XS Rating Curve= 0 ,0
Exp/Cntr(USF)=0,0
Exp/Cntr=0.3,0.1

Type RM Length L Ch R = 1 ,3336    ,159,159.1,159.5
XS GIS Cut Line= 2
2299739.19565713605236.5815723222300188.17650315605619.046737454
#Sta/Elev= 30
       0 3688.24    13.3 3679.57    18.1 3678.62    38.1 3678.67    43.7 3676.56
    60.7 3666.58    74.9 3660.41    97.6  3652.1   116.9 3647.39   127.4 3646.12
   148.4 3640.84   179.8 3636.57     201 3635.09     222 3635.71   239.5 3633.43
   250.8 3634.66  257.323633.961     265 3632.78   276.4 3633.94   284.7 3635.51
   306.1 3636.37   364.9 3636.47   426.9 3638.02   463.7 3641.91   511.9 3651.21
   525.2 3651.96   537.4 3656.36   547.8 3658.14   557.3 3661.15   589.8 3666.48
#Mann= 5 ,-1,0
       0     .06       0     150     .12       0  257.32    .045       0
   276.4     .12       0     280      .1       0
#XS Ineff= 2 , 0
          222.24  3639.1
Permanent Ineff=
       F       F
Bank Sta=257.32,276.4
XS Rating Curve= 0 ,0
Exp/Cntr(USF)=0,0
Exp/Cntr=0.3,0.1

Type RM Length L Ch R = 1 ,3177    ,195.8,196.8,195.6
XS GIS Cut Line= 2
2299646.58207522605348.3663473442300067.87472581605744.631711759
#Sta/Elev= 30
       0 3674.36    12.9 3673.73    15.9 3672.82    30.4 3664.74    52.6 3656.57
    62.6 3654.18    72.4 3650.77     123 3639.52   137.5 3636.78   165.8 3633.25
   194.4 3632.25   202.6  3630.4   219.6 3629.47   228.9 3627.36   242.2 3626.64
   252.2 3627.34   259.2 3628.47   287.7 3629.59   345.6 3630.22   380.7 3631.98
   392.2 3631.85     414 3633.07   441.5 3635.89   485.4 3645.07   496.9 3644.96
   507.4 3649.25   513.9 3651.09   538.3 3656.73     550 3658.64   578.4  3666.7
#Mann= 9 ,-1,0
       0     .06       0     120     .12       0     150      .1       0
   228.9    .045       0   252.2      .1       0     260     .12       0
     290      .1       0     550     .12       0     560      .1       0
Bank Sta=228.9,252.2
XS Rating Curve= 0 ,0
Exp/Cntr(USF)=0,0
Exp/Cntr=0.3,0.1

Type RM Length L Ch R = 1 ,2980    ,144.8,146.8,146.1
XS GIS Cut Line= 4
2299573.66380442605420.2206803212299599.14896321605575.462253896
2299828.30767028605769.4759606862299965.08982831605824.559676649
#Sta/Elev= 30
       0 3670.62      10 3666.11    62.2 3649.63    72.7 3647.77   102.3 3639.27
   118.5 3636.27   130.7 3632.26     155 3626.82   184.9 3622.36   211.1 3621.64
   221.6 3622.39   241.9 3617.39   250.1 3615.93  257.57  3617.4   264.3 3618.16
   277.6 3617.15   296.2  3619.9   335.2 3620.83   364.3 3623.18   394.8 3623.37
   440.2 3627.69   466.5 3631.62   478.8 3634.97   484.9 3634.62   500.6    3636
   515.7 3638.88     528 3639.28   542.4 3643.42   591.1 3651.98     605 3655.55
#Mann= 7 ,-1,0
       0     .06       0      10     .12       0   241.9    .045       0
  257.57     .12       0  367.32      .1       0  387.32     .12       0
  597.58      .1       0
Bank Sta=241.9,257.57
XS Rating Curve= 0 ,0
Exp/Cntr=0.3,0.1

Type RM Length L Ch R = 1 ,2833    ,183.8,182.6,178.8
XS GIS Cut Line= 4
2299499.27816361605515.6243206292299504.61017098605670.791778464
 2299644.6432815605799.3383998982299939.45504116605926.208996957
#Sta/Elev= 30
       0 3652.62    17.6 3647.53    37.6 3644.49    45.6 3640.92    77.6 3630.64
    89.6 3625.07    97.6 3623.75   125.6 3616.29   130.1 3617.03   159.5 3615.16
   165.5 3613.96   238.7 3613.03   264.2 3609.16   286.9  3607.5   300.7 3605.83
   306.7 3607.51   312.6  3611.6     318 3613.71   329.3 3613.68   337.8 3615.43
   379.7 3617.61   420.8 3620.95   466.8 3626.38   510.3  3633.9     519 3636.17
   532.1 3636.12   545.2 3641.11     596  3651.3   619.2 3654.17   666.3 3665.59
#Mann= 7 ,-1,0
       0     .12       0  235.26      .1       0   286.9    .045       0
   306.7      .1       0  365.35     .12       0  405.35      .1       0
  465.35     .12       0
Bank Sta=286.9,306.7
XS Rating Curve= 0 ,0
Exp/Cntr=0.3,0.1

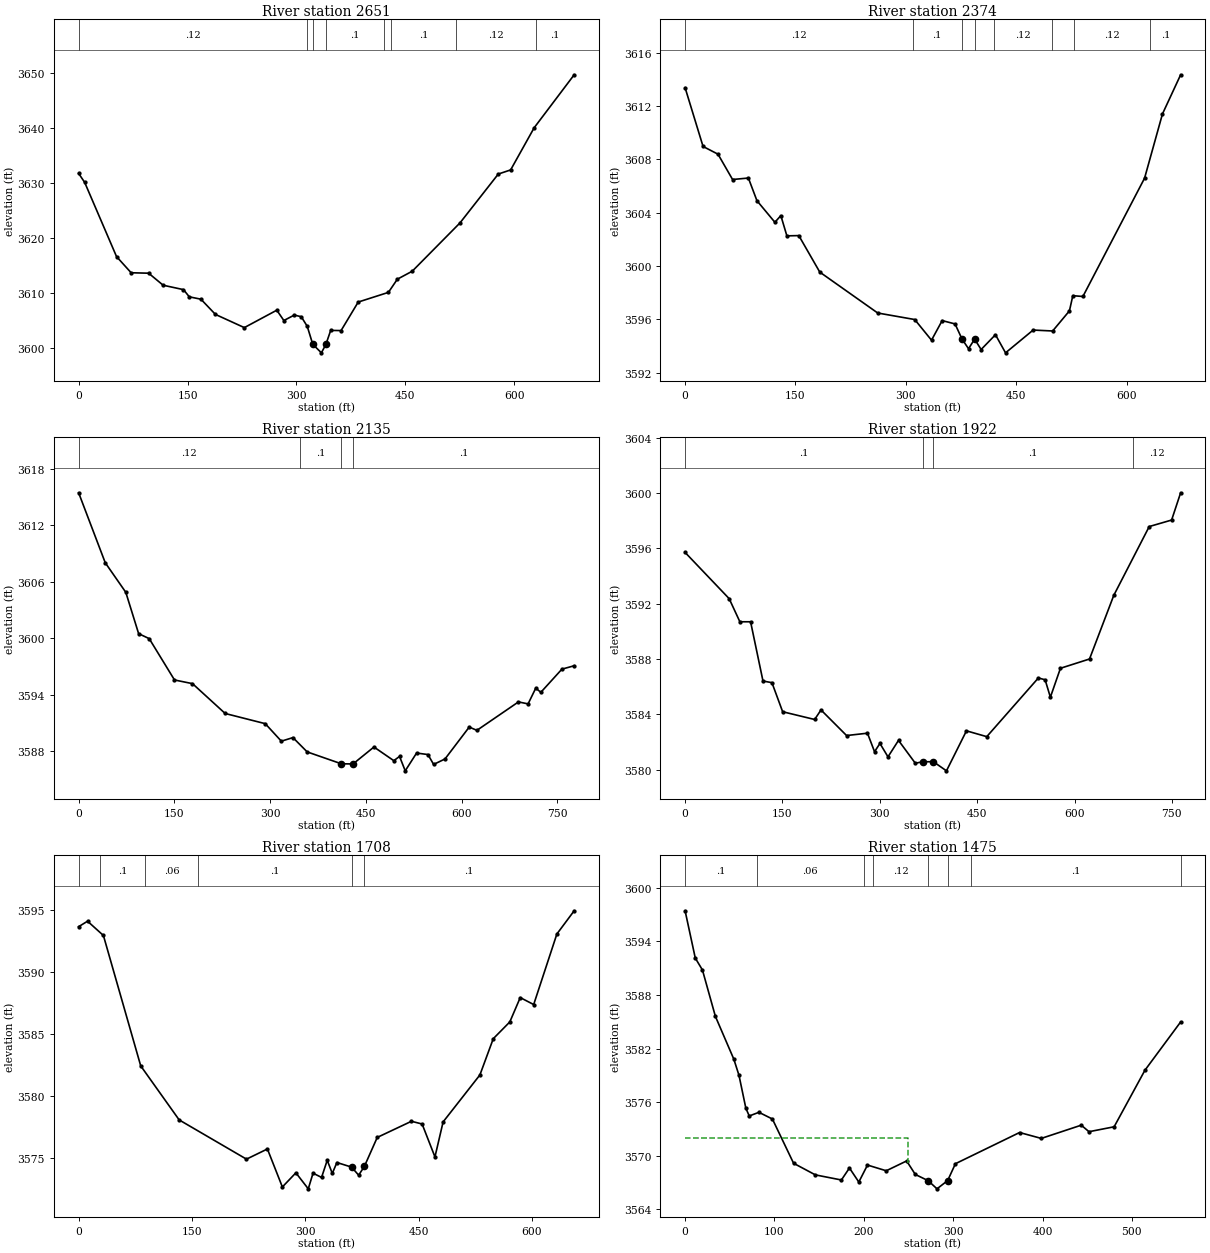
Type RM Length L Ch R = 1 ,2651    ,271.8,277.1,281.5
XS GIS Cut Line= 4
 2299394.2236063605604.8960306232299384.83837399605829.098802594
2299528.74526949605911.4802862492299813.43064971605977.176912455
#Sta/Elev= 30
       0  3631.7     8.3 3630.08    52.2 3616.57    72.3 3613.63    96.4 3613.55
   116.4 3611.36   144.4 3610.56   152.4 3609.25   168.4 3608.82   188.4 3606.05
   228.2 3603.65   272.9 3606.82   282.6 3604.94     297 3605.93   306.6 3605.63
   314.8 3603.89   322.4 3600.62   334.3 3599.06  340.55 3600.61   347.1 3603.14
   361.4 3603.11     385  3608.3   426.6 3610.06   438.9 3612.46   459.4 3613.91
   525.1 3622.69   577.9 3631.59   594.9 3632.34   627.3 3640.01   682.4 3649.65
#Mann= 8 ,-1,0
       0     .12       0   314.4      .1       0   322.4    .045       0
  340.55      .1       0  420.22     .12       0  430.22      .1       0
  520.22     .12       0  630.22      .1       0
Bank Sta=322.4,340.55
XS Rating Curve= 0 ,0
Exp/Cntr(USF)=0,0
Exp/Cntr=0.3,0.1

Type RM Length L Ch R = 1 ,2374    ,238.6,238.8,239.4
XS GIS Cut Line= 4
2299288.43420808605725.2136991942299243.08260747 605970.11234248
 2299394.2546095606243.7336661522299504.61017098606260.362586375
#Sta/Elev= 30
       0 3613.38    24.4 3608.97    44.7 3608.39    64.5 3606.49      86  3606.6
    97.6  3604.9     122 3603.28   130.1 3603.78   138.3 3602.26   154.5 3602.28
     183 3599.54   261.7 3596.47     312 3595.98   334.8 3594.43   349.3  3595.9
   366.8 3595.65  376.293594.511   385.1 3593.79   393.4 3594.51   402.2 3593.73
   421.7 3594.84   435.4 3593.48   472.9 3595.19   499.4 3595.12   522.2 3596.63
   526.8 3597.77   540.5 3597.71   624.3 3606.59   648.6 3611.41   673.3 3614.35
#Mann= 8 ,-1,0
       0     .12       0  309.06      .1       0  376.29    .045       0
   393.4      .1       0  419.06     .12       0  499.06      .1       0
  529.06     .12       0  631.67      .1       0
Bank Sta=376.29,393.4
XS Rating Curve= 0 ,0
Exp/Cntr(USF)=0,0
Exp/Cntr=0.3,0.1

Type RM Length L Ch R = 1 ,2135    ,216.7,212.5,209.7
XS GIS Cut Line= 4
2299026.49084045605783.6760406492299004.23084427606009.417063008
2299171.84691972606351.3886427792299340.24783943606361.356397363
#Sta/Elev= 30
       0 3615.45    41.7 3608.02    73.9 3604.88      94 3600.49   110.6 3599.96
   150.2 3595.57   178.4 3595.18   229.6 3592.01   292.4 3590.93   317.6 3589.07
   335.8 3589.45   358.1 3587.93   411.53586.671   429.9 3586.65   462.7 3588.45
   493.8    3587   502.8 3587.45   511.7 3585.92   529.5 3587.81   547.3 3587.65
   556.2  3586.6     574 3587.18     612 3590.57     624 3590.22   689.1 3593.24
   704.2 3593.03   716.2  3594.7   724.2 3594.26   757.2 3596.72   776.4 3597.08
#Mann= 4 ,-1,0
       0     .12       0  346.84      .1       0   411.5    .045       0
   429.9      .1       0
Bank Sta=411.5,429.9
XS Rating Curve= 0 ,0
Exp/Cntr=0.3,0.1

Type RM Length L Ch R = 1 ,1922    ,213.3,213.8,214.1
XS GIS Cut Line= 4
2298724.83984038606031.230065722  2298760.843921606177.217985259
2299156.18690265606515.1643564612299208.62384407606592.031047378
#Sta/Elev= 30
       0  3595.7    67.9 3592.36    84.4 3590.69   100.9 3590.69     120 3586.41
   133.8 3586.29   150.3 3584.19   199.6 3583.63   209.4 3584.32   248.8 3582.47
     281 3582.64   291.9  3581.3   300.2  3581.9   312.6 3580.93   328.8 3582.12
   354.7 3580.47  366.313580.575   382.5 3580.58   402.7 3579.92   433.5 3582.81
   464.8 3582.39   544.3 3586.63   554.7  3586.5   562.8 3585.24   578.3 3587.33
   623.1    3588   660.5  3592.6   715.1 3597.57   749.6 3598.04   763.5 3600.01
#Mann= 4 ,-1,0
       0      .1       0  366.31    .045       0   382.5      .1       0
  690.46     .12       0
Bank Sta=366.31,382.5
XS Rating Curve= 0 ,0
Exp/Cntr(USF)=0,0
Exp/Cntr=0.3,0.1

Type RM Length L Ch R = 1 ,1708    ,235.1,233.1,231.4
XS GIS Cut Line= 3
2298555.01802126606260.0316389982298561.29687832606264.897746436
2299040.45327055606701.302614673
#Sta/Elev= 30
       0 3593.66    11.8  3594.1    32.8 3592.95    82.2 3582.45   133.1  3578.1
   222.2 3574.94   249.9 3575.76   269.7  3572.7   287.6 3573.84     304 3572.55
   310.3 3573.81   321.6 3573.47   329.1 3574.85   335.8 3573.79   341.9 3574.67
   361.3  3574.3   370.7 3573.65   378.3 3574.36   395.3 3576.69   440.6 3577.99
   454.7 3577.77   471.7 3575.12   482.5 3577.94   531.2 3581.72   548.9 3584.64
   570.8 3585.99   584.6 3587.95   602.4 3587.39   633.1 3593.07     656 3594.94
#Mann= 6 ,-1,0
       0     .06       0   27.94      .1       0   87.94     .06       0
  157.94      .1       0   361.3    .045       0   378.3      .1       0
Bank Sta=361.3,378.3
XS Rating Curve= 0 ,0
Exp/Cntr(USF)=0,0
Exp/Cntr=0.3,0.1

Type RM Length L Ch R = 1 ,1475    ,196.5,196.6,196.1
XS GIS Cut Line= 2
2298412.25106304606489.2180761022298868.49723548606804.402630011
#Sta/Elev= 30
       0 3597.41    11.4 3592.12    19.4 3590.79    33.9  3585.6    54.5 3580.82
    60.3 3579.01      68 3575.32    71.8 3574.46    82.6 3574.87    97.7 3574.12
   121.4 3569.17   145.8 3567.87   174.9  3567.3   183.9 3568.64   194.4 3567.07
   204.1 3568.97   225.1 3568.33   247.9 3569.43   257.6 3567.92  272.063567.219
   281.9 3566.31  293.843567.239   302.5 3569.12   374.3 3572.61   398.6 3571.95
   443.3 3573.43     452  3572.7   480.1 3573.25   514.6 3579.58   554.5 3584.97
#Mann= 8 ,-1,0
       0      .1       0      80     .06       0     200      .1       0
     210     .12       0  272.06    .045       0  293.84     .12       0
     320      .1       0  554.53     .12       0
#XS Ineff= 2 , 0
           249.1    3572
Permanent Ineff=
       F       F
Bank Sta=272.06,293.84
XS Rating Curve= 0 ,0
Exp/Cntr(USF)=0,0
Exp/Cntr=0.3,0.1

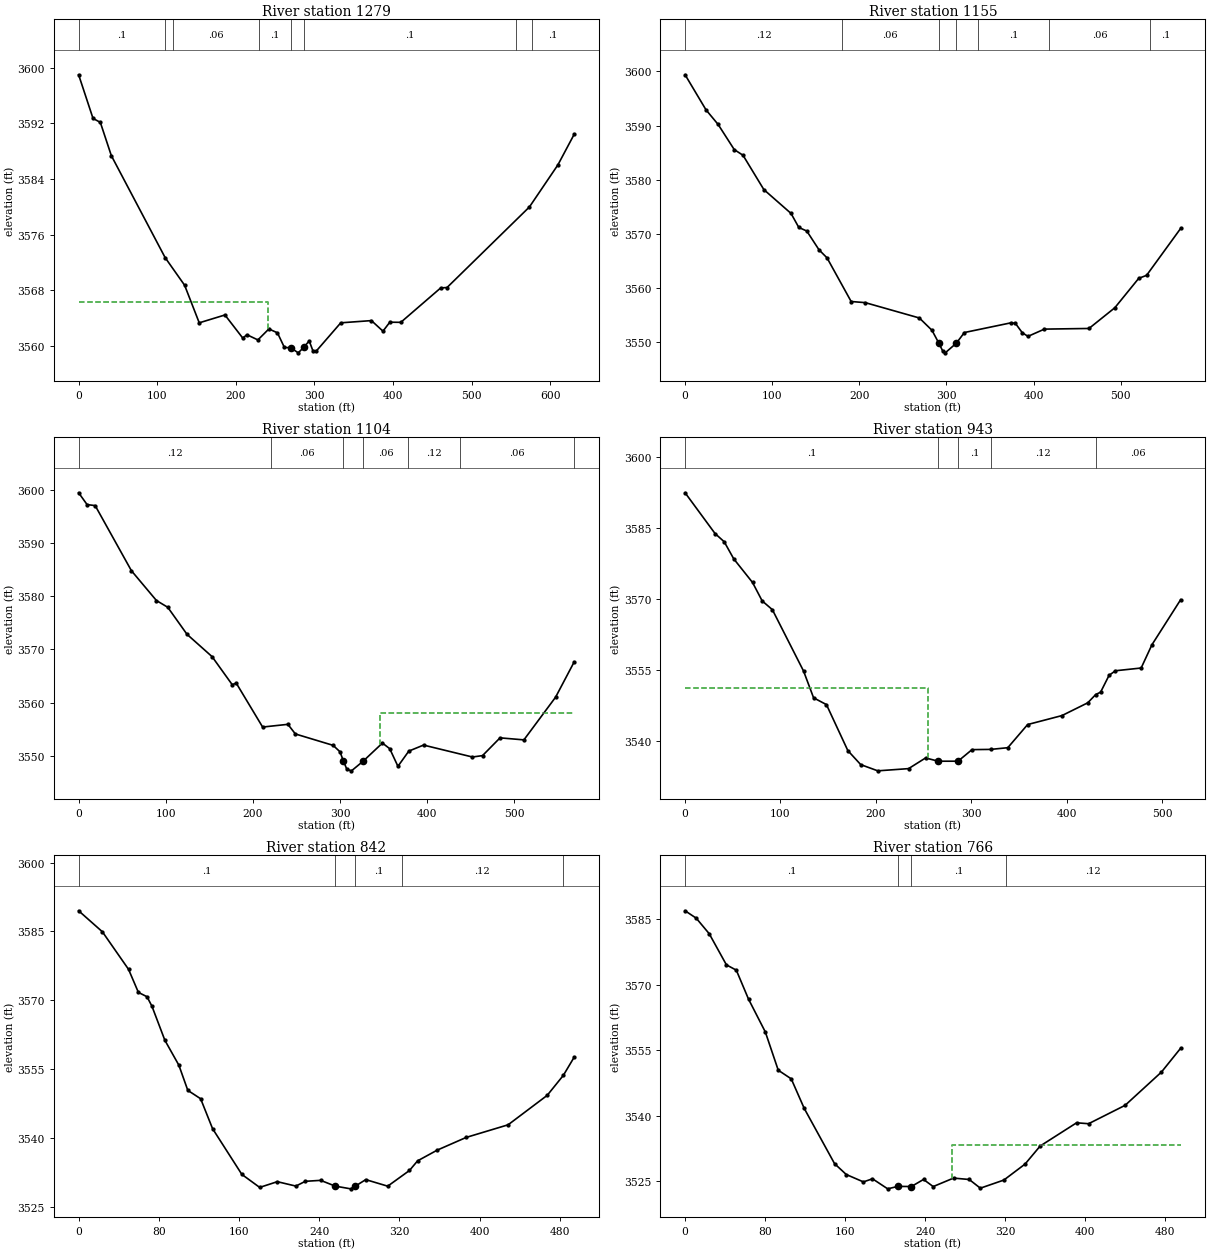
Type RM Length L Ch R = 1 ,1279    ,119.4,123.7,130.7
BEGIN DESCRIPTION:
Structure XS 4
END DESCRIPTION:
XS GIS Cut Line= 3
2298280.50937158606653.9564427322298672.60352163606888.587250609
2298844.66611407 606909.44332242
#Sta/Elev= 30
       0 3599.01    18.3 3592.73    27.6 3592.16    41.6 3587.37     110  3572.7
   134.8 3568.72   153.4 3563.31   186.1 3564.44   208.8 3561.11     214  3561.6
     228 3560.85     242 3562.43   252.9 3561.87   261.7 3559.77     270 3559.71
   279.3 3558.99  286.18 3559.76   293.3 3560.71   297.9 3559.31   302.3 3559.25
   333.4 3563.31   372.4 3563.63   387.1 3562.11   395.8  3563.4   409.8 3563.38
   460.5 3568.33   468.6 3568.39   573.4 3579.99   609.6 3586.04   630.3 3590.44
#Mann= 8 ,-1,0
       0      .1       0     110     .12       0     120     .06       0
     230      .1       0     270    .045       0  286.18      .1       0
  556.93     .12       0  576.93      .1       0
#XS Ineff= 2 , 0
          241.08 3566.29
Permanent Ineff=
       F       F
Bank Sta=270,286.18
XS Rating Curve= 0 ,0
Exp/Cntr(USF)=0,0
Exp/Cntr=0.3,0.1

Type RM Length L Ch R = 1 ,1155    ,52,51.6,52.7
BEGIN DESCRIPTION:
Structure XS 3
END DESCRIPTION:
XS GIS Cut Line= 6
2298227.40945129606719.7355845512298400.49464189606820.436869473
2298448.88280548606891.595933576 2298484.9367313606953.267122465
2298518.14429454607053.8385997312298610.51123674607104.050610458
#Sta/Elev= 30
       0 3599.39      24  3592.9    37.9  3590.2    56.4 3585.55    66.5 3584.49
    90.4 3578.14   121.6 3573.73   130.5 3571.14   139.7 3570.47   153.7    3567
   162.9 3565.51   190.6 3557.43   206.8 3557.22   268.9 3554.38   283.4  3552.1
  291.21 3549.73   295.7 3548.28   298.6 3547.93   311.3 3549.71   320.6 3551.69
   374.5  3553.5   379.2 3553.37   387.1 3551.64   393.6 3550.98   412.4 3552.32
   463.6 3552.44   493.3 3556.28   520.7 3561.72   529.7 3562.27   568.8 3570.95
#Mann= 7 ,-1,0
       0     .12       0     180     .06       0  291.21    .045       0
   311.3     .06       0   336.3      .1       0  417.74     .06       0
  533.65      .1       0
Bank Sta=291.21,311.3
XS Rating Curve= 0 ,0
Exp/Cntr(USF)=0,0
Exp/Cntr=0.3,0.1

Type RM Length L Ch R = 1 ,1104    ,165.6,160.9,151.6
BEGIN DESCRIPTION:
Structure XS 2
END DESCRIPTION:
XS GIS Cut Line= 6
2298191.79426469606751.4181987362298364.87945529606852.119483658
2298413.26761888606923.278547761 2298449.3215447 606984.94973665
2298482.52910794607085.5212139162298574.89605014607135.733224644
#Sta/Elev= 30
       0 3599.44     9.7 3597.22      19 3597.03    60.6 3584.79    89.3 3579.19
   102.3 3577.92   124.4 3572.84   153.2 3568.64   176.3 3563.37   180.9 3563.67
   211.2 3555.41   240.2 3555.92   248.8 3554.11   292.1 3551.97     300 3550.76
  303.99    3549   307.9 3547.46   313.2 3547.18  326.61    3549   348.7  3552.4
   357.1 3551.34   366.5 3548.03     379 3550.89   395.9 3552.02     452 3549.78
   463.6 3550.04   483.7 3553.38   511.1    3553   547.5 3561.03   568.8 3567.65
#Mann= 7 ,-1,0
       0     .12       0  220.25     .06       0  303.99    .045       0
  326.61     .06       0  377.74     .12       0  437.74     .06       0
  568.78      .1       0
#XS Ineff= 2 , 0
                          346.14          3558.1
Permanent Ineff=
       F       F
Bank Sta=303.99,326.61
XS Rating Curve= 0 ,0
Exp/Cntr(USF)=0,0
Exp/Cntr=0.3,0.1

Type RM Length L Ch R = 1 ,943     ,95.4,100.6,104.2
BEGIN DESCRIPTION:
Structure XS 1 IFA to wet channel
END DESCRIPTION:
XS GIS Cut Line= 2
2298096.20950872606954.0103814932298558.91195483607190.127612857
#Sta/Elev= 30
       0 3592.49    31.4 3583.86      41 3582.12      51  3578.5    70.7  3573.5
    80.8  3569.6    91.5 3567.74   124.2 3554.74   134.7 3549.08   148.2 3547.64
   170.6 3537.91   184.1 3534.94     202 3533.62   234.3 3534.09   252.1 3536.35
  265.37 3535.66   286.1 3535.66   300.8 3538.11   320.5 3538.16   338.3 3538.52
   359.1 3543.42   395.1 3545.32   422.1 3548.02   430.5 3549.78   435.6 3550.28
   444.5 3553.85   451.2 3554.81   478.1 3555.39   489.4 3560.31   519.5 3569.85
#Mann= 5 ,-1,0
       0      .1       0  265.37    .045       0   286.1      .1       0
   320.5     .12       0   430.5     .06       0
#XS Ineff= 2 , 0
          255.15 3551.22
Permanent Ineff=
       F       F
Bank Sta=265.37,286.1
XS Rating Curve= 0 ,0
Exp/Cntr(USF)=0,0
Exp/Cntr=0.3,0.1

Type RM Length L Ch R = 1 ,842     ,74.8,75.5,77.3
XS GIS Cut Line= 4
2298067.04836294607006.6304540912298215.88013744607082.262304842
2298316.92754776607200.731682466 2298486.8352515607225.169393335
#Sta/Elev= 30
       0 3589.48    23.7  3584.9    49.8 3576.71    59.6 3571.69    68.2 3570.74
    73.1 3568.69      86 3561.26     100 3555.81   108.9 3550.33   121.7  3548.5
   133.6 3541.98   162.8 3532.01   180.6 3529.17   198.2 3530.42   216.7 3529.46
   226.1  3530.5   241.4 3530.71255.99413529.452   271.4 3528.86   275.9 3529.43
   286.4 3530.87   308.3 3529.44     330 3532.86   338.1 3534.96   357.7  3537.3
   386.6 3540.07   428.4 3542.82   467.4 3549.24   483.5  3553.6   494.3 3557.56
#Mann= 5 ,-1,0
       0      .1       0255.9941    .045       0   275.9      .1       0
  322.66     .12       0  482.66     .06       0
Bank Sta=255.9941,275.9
XS Rating Curve= 0 ,0
Exp/Cntr(USF)=0,0
Exp/Cntr=0.3,0.1

Type RM Length L Ch R = 1 ,766     ,99.2,95.4,92.5
XS GIS Cut Line= 4
2298029.89154465607080.7995639692298172.43125929607138.761771584
2298262.33182621607254.6861868152298455.14488419607281.892937328
#Sta/Elev= 30
       0  3586.9    11.1 3585.21    24.1 3581.65    41.3 3574.52    51.2  3573.3
    63.4 3566.67    80.2 3559.15    93.1  3550.4   106.1 3548.42   119.1 3541.64
   149.4    3529   161.1 3526.52   178.2 3524.83   187.3 3525.54   202.5 3523.24
   212.6  3523.8  226.173523.769   238.3 3525.39     248 3523.76   268.3  3525.7
     284 3525.38   295.1 3523.39   318.6 3525.25   339.8 3528.91   354.9 3533.04
   391.3 3538.36   403.3 3538.15   439.8 3542.36   476.1 3549.97   495.3 3555.43
#Mann= 4 ,-1,0
       0      .1       0   212.6    .045       0  226.17      .1       0
  320.57     .12       0
#XS Ineff= 2 , 0
                          266.79         3533.28
Permanent Ineff=
       F       F
Bank Sta=212.6,226.17
XS Rating Curve= 0 ,0
Exp/Cntr(USF)=0,0
Exp/Cntr=0.3,0.1