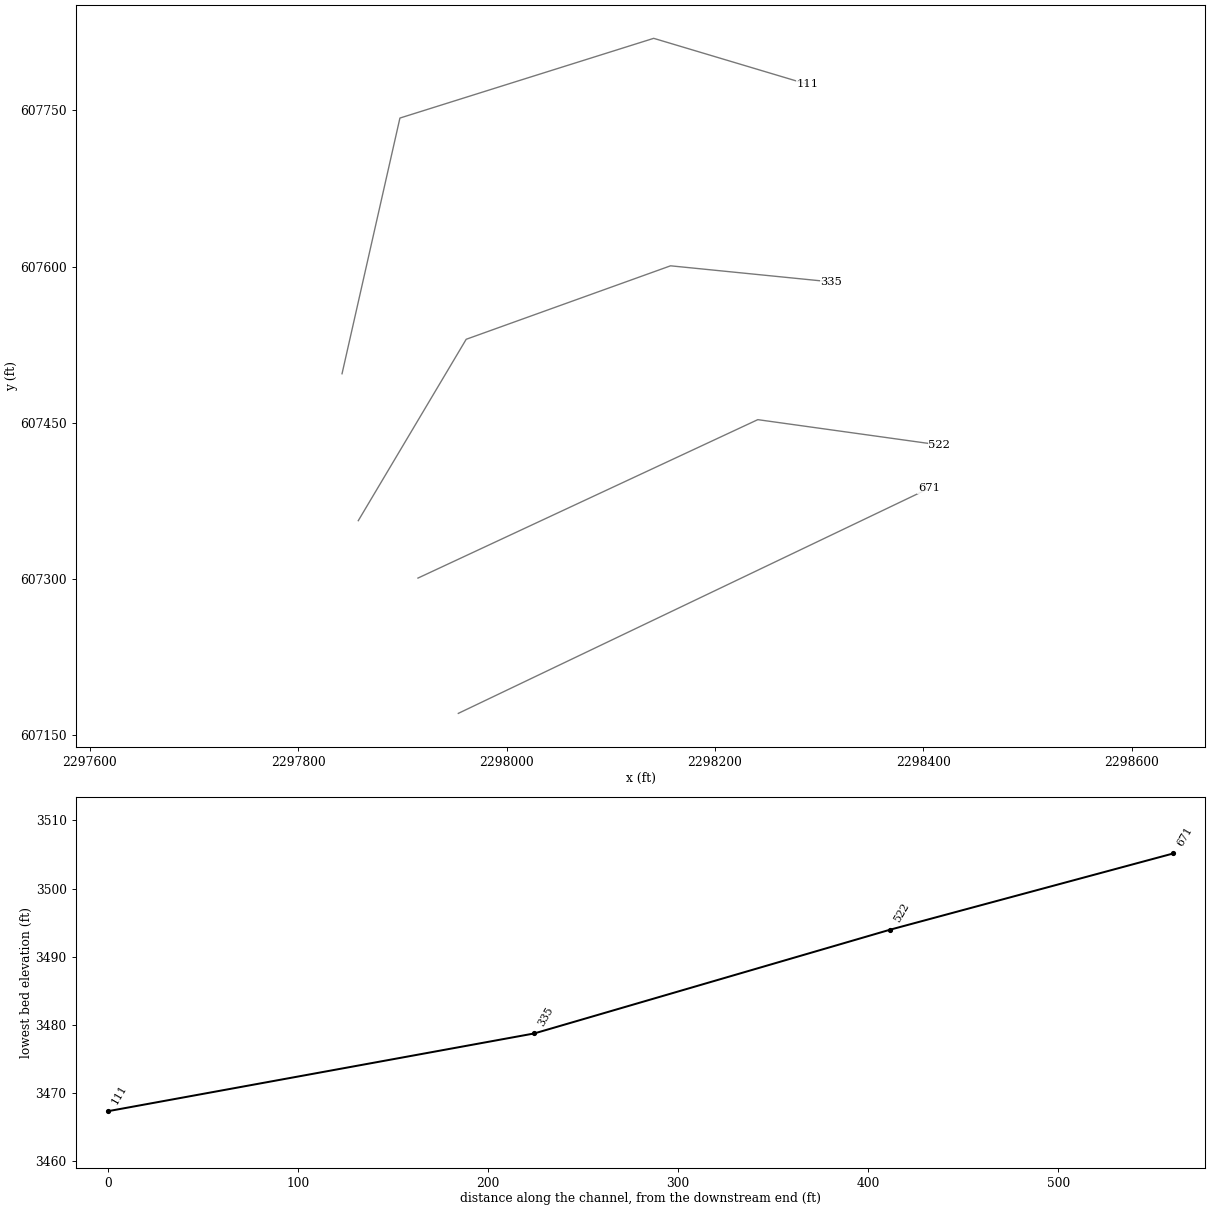
HEC-RAS study GLADERN.prj: GLADERN

--- GLADERN.g01 (geometry) --- (continued)

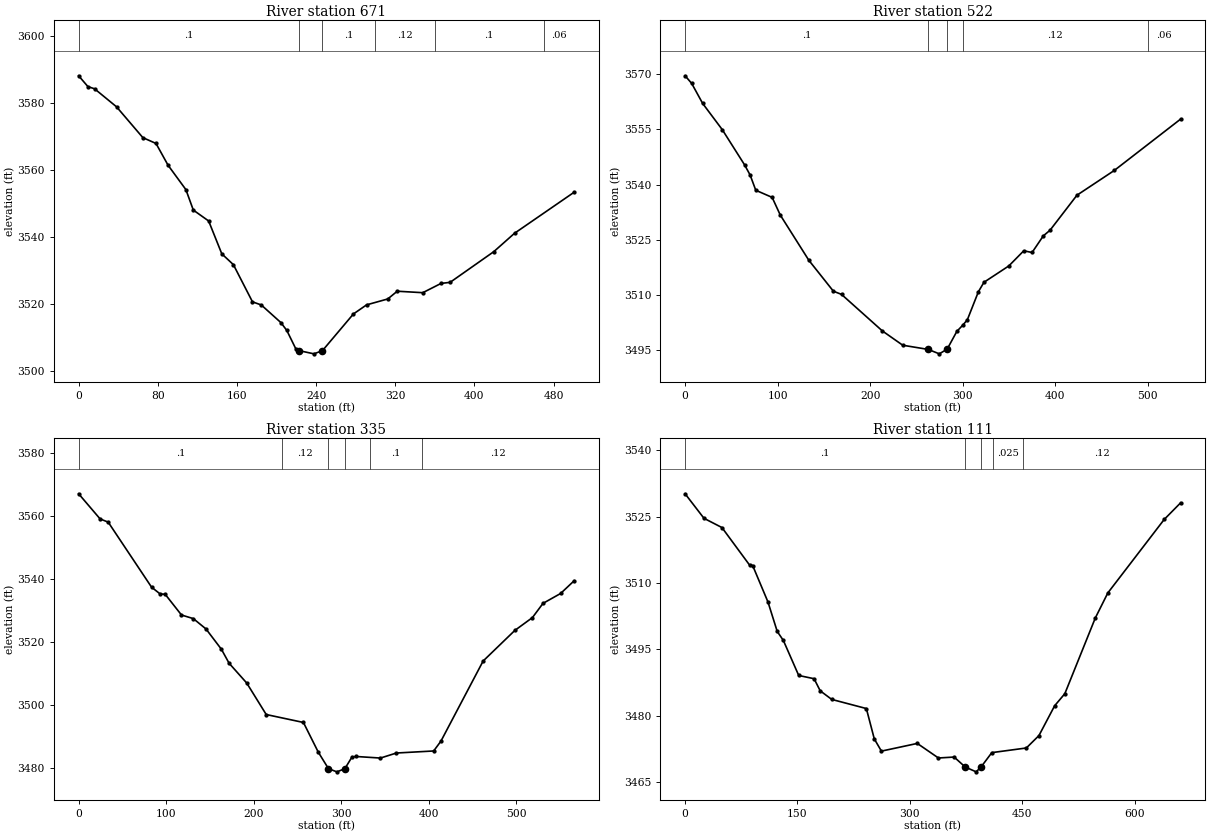
Type RM Length L Ch R = 1 ,671     ,148.7,148.9,146.4
XS GIS Cut Line= 2
2297953.64161881607171.1732489152298405.47961567607387.173852293
#Sta/Elev= 30
       0 3588.05     9.4 3584.82    16.1 3584.17    38.3  3578.8    64.9 3569.61
    78.2 3567.87    90.4 3561.37   108.4 3554.11   115.9 3548.01   131.4 3544.76
   144.7 3534.96   156.4 3531.74   175.7 3520.65   184.6 3519.72   204.4 3514.47
   210.4 3512.12   219.4 3506.69   222.4 3506.13   237.8 3505.15   246.4  3506.1
   277.7 3517.04     291 3519.75   312.4 3521.51     322 3523.82   347.8 3523.38
   366.3 3526.15   375.4 3526.46   419.6 3535.62   440.5 3541.09   500.8 3553.34
#Mann= 6 ,-1,0
       0      .1       0   222.4    .045       0   246.4      .1       0
     300     .12       0     360      .1       0     470     .06       0
Bank Sta=222.4,246.4
XS Rating Curve= 0 ,0
Exp/Cntr(USF)=0,0
Exp/Cntr=0.3,0.1

Type RM Length L Ch R = 1 ,522     ,187.1,187.3,185.9
XS GIS Cut Line= 3
 2297914.9109936  607301.05382882298241.11598646607453.135886281
2298415.23892183607428.890920595
#Sta/Elev= 30
       0 3569.61     7.1 3567.54      19 3562.08    40.2 3554.95    64.3 3545.38
    70.3 3542.61    76.4 3538.47    94.1 3536.53   102.9 3531.72   133.8 3519.41
   160.3 3511.01   169.1 3510.14   213.2 3500.21   235.3 3496.31   262.9 3495.17
   274.8 3493.97  283.313495.251   293.8 3500.09     300 3501.72   305.1 3503.22
   317.1 3510.88   323.1 3513.44     350 3517.89   366.1    3522   375.1 3521.54
   387.2 3526.05   394.5 3527.59   423.6 3537.12     464 3543.86   535.7 3557.83
#Mann= 5 ,-1,0
       0      .1       0   262.9    .045       0  283.31      .1       0
     300     .12       0  499.91     .06       0
Bank Sta=262.9,283.31
XS Rating Curve= 0 ,0
Exp/Cntr(USF)=0,0
Exp/Cntr=0.3,0.1

Type RM Length L Ch R = 1 ,335     ,224.6,224.3,224.2
XS GIS Cut Line= 4
2297857.60471107607356.1560235392297961.19683718607530.278958916
2298157.36065045607600.8097681822298311.64679572607585.381153655
#Sta/Elev= 30
       0 3567.09    24.5 3559.11    33.8 3558.07    83.3 3537.42    93.1 3535.26
    98.9 3535.15   117.5 3528.57     131 3527.43   145.5 3524.14   163.1 3517.69
   171.9 3513.24     192 3506.97   214.3 3496.95   256.8 3494.43   273.8 3484.98
   285.4 3479.75     295 3478.74   304.1 3479.72     312 3483.33   316.3 3483.63
   344.8 3483.12     363 3484.72   405.6 3485.37   413.9  3488.5   462.1 3513.95
   498.3 3523.67   518.4 3527.75   530.5 3532.27   550.6 3535.41   566.1 3539.46
#Mann= 6 ,-1,0
       0      .1       0  232.61     .12       0   285.4    .045       0
   304.1     .12       0  332.61      .1       0  392.61     .12       0
Bank Sta=285.4,304.1
XS Rating Curve= 0 ,0
Exp/Cntr(USF)=0,0
Exp/Cntr=0.3,0.1

Type RM Length L Ch R = 1 ,111     ,,,
XS GIS Cut Line= 4
2297842.00234579607497.1932634332297897.57717121607742.651984479
2298141.19146243 607819.178663892298289.30191881607774.922023789
#Sta/Elev= 30
       0 3530.15    25.2 3524.61    49.2 3522.52    86.1 3514.04    90.2 3513.94
   110.7 3505.68     123 3499.05   131.2 3497.01   151.7  3489.1   172.2 3488.37
   180.4 3485.63   195.8 3483.69     242 3481.63   252.6 3474.77   262.1 3472.01
     310 3473.75   338.2 3470.46   359.2 3470.67     374 3468.42   388.6 3467.33
   395.33468.465   409.5 3471.67   455.6 3472.72   472.4 3475.52   493.4 3482.26
     507 3484.99   547.7  3502.1   564.4 3507.75   639.6 3524.34   661.6 3528.11
#Mann= 5 ,-1,0
       0      .1       0     374    .045       0   395.3      .1       0
  411.67    .025       0  451.67     .12       0
Bank Sta=374,395.3
XS Rating Curve= 0 ,0
Exp/Cntr(USF)=0,0
Exp/Cntr=0.3,0.1
LCMann Table=0

Chan Stop Cuts=-1
Use User Specified Reach Order=0
Composite Channel Slope=5